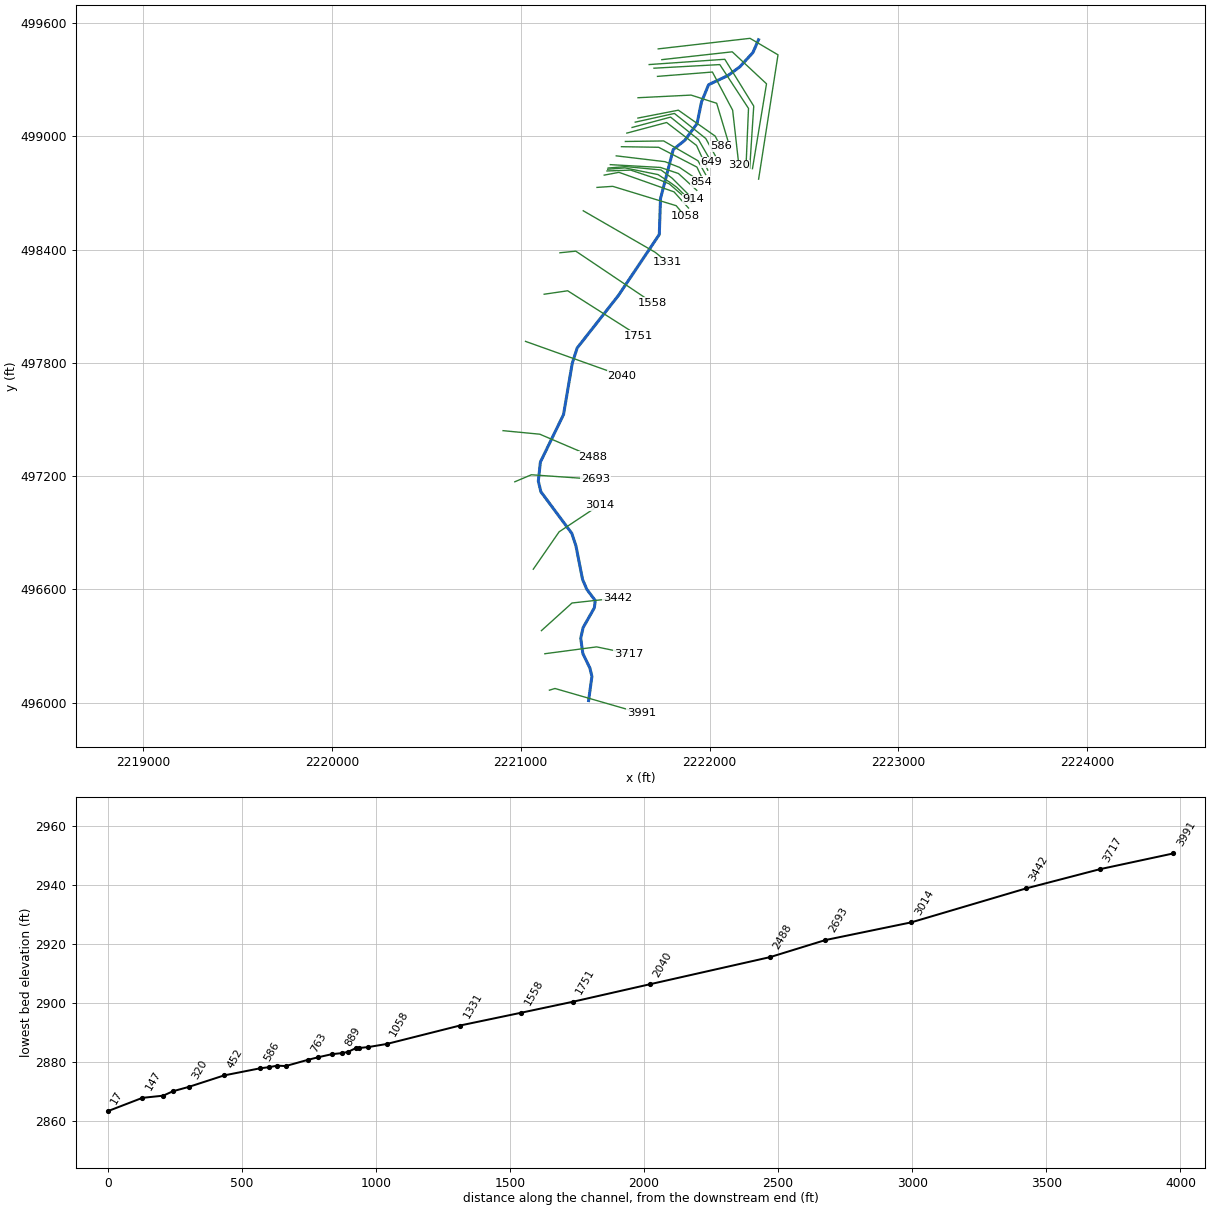
--- MILLCK.prj (project) ---

Proj Title=MILLCK
Current Plan=p01
Default Exp/Contr=0,0
English Units
Geom File=g01
Flow File=f01
Plan File=p01
Background Map Layer=Inundation Boundary (01pct Value_0)
BEGIN DESCRIPTION:
----------MODEL BY WOOD PLC 2021----------
Stream Name: Mill Creek
Flood Zone: Enhanced Approximate
Pocahontas County, WV
HEC-RAS Version: RAS 6.1
Vertical Datum: NAVD88
Projection: NAD 1983 StatePlane West Virginia S FIPS 4702 (US Feet)
Terrain: 1-meter LIDAR (FEMA Region III 3DEP collected 2016-2018)
Land Use: 2019 NLCD
Hydrologic Method:
WV SIR2010-5033 regression equations
END DESCRIPTION:
DSS Export Rating Curves= 0
DSS Export Rating Curve Sorted= 0
DSS Export Volume Flow Curves= 0
DXF OffsetX= 0
DXF OffsetY= 0
DXF ScaleX= 0
DXF ScaleY= 0

--- MILLCK.p01 (plan) ---

Plan Title=Floodplain
Program Version=6.10
Short Identifier=Floodplain
Geom File=g01
Flow File=f01
Subcritical Flow
K Sum by GR= 0
Std Step Tol= 0.01
Critical Tol= 0.01
Num of Std Step Trials= 20
Max Error Tol= 0.3
Flow Tol Ratio= 0.001
Split Flow NTrial= 30
Split Flow Tol= 0.02
Split Flow Ratio= 0.02
Log Output Level= 0
Friction Slope Method= 1
Unsteady Friction Slope Method= 2
Unsteady Bridges Friction Slope Method= 1
Parabolic Critical Depth
Global Vel Dist= 0 , 0 , 0
Global Log Level= 0
CheckData=True
Encroach Param=-1 ,0,0, 0
Mapping Interval=1HOUR
Computation Time Step Use Courant=        0
Computation Time Step Use Time Series=    0
Computation Time Step Count To Double=0
Computation Time Step Max Doubling=0
Computation Time Step Max Halving=0
Computation Time Step Residence Courant=0
Run HTab= 0
Run UNet= 0
Run Sediment= 0
Run PostProcess= 0
Run WQNet= 0
Run RASMapper=-1
UNET Theta= 0
UNET Theta Warmup= 0
UNET ZTol= 0
UNET ZSATol= 0
UNET MxIter= 0
UNET Max Iter WO Improvement= 0
UNET MaxInSteps= 0
UNET DtIC= 0
UNET DtMin= 0
UNET MaxCRTS= 0
UNET WFStab= 0
UNET SFStab= 0
UNET WFX= 1
UNET SFX= 1
UNET Gravity=32.174
UNET 1D Methodology=Finite Difference
UNET DSS MLevel= 1
UNET Pardiso=0
UNET DZMax Abort= 0
UNET Use Existing IB Tables= 0
UNET Froude Reduction=False
UNET Froude Limit= 0
UNET Froude Power= 0
UNET D1 Cores= 0
UNET WindReference=Eulerian
UNET WindDragFormulation=Hsu (1988)
UNET D2 Coriolis=0
UNET D2 Cores= 0
UNET D2 Theta= 1
UNET D2 Theta Warmup= 1
UNET D2 Z Tol= 0.01
UNET D2 Volume Tol= 0.01
UNET D2 Max Iterations= 20
UNET D2 Equation= 0
UNET D2 RampUpFraction=0.1
UNET D2 TimeSlices= 1
UNET D2 Turbulence Formulation=Non-Conservative (original)
UNET D2 Eddy Viscosity=0.3
UNET D2 Transverse Eddy Viscosity=0.1
UNET D2 Smagorinsky Mixing=0
UNET D2 BCVolumeCheck=0
UNET D2 Cores=0
UNET D2 SolverType=PARDISO (Direct)
UNET D2 Minimum Iterations= 2147483647
UNET D2 Maximum Iterations= 2147483647
UNET D2 Restart Number= 10
UNET D2 Relaxation Coeff=1.3
UNET D2 SOR Precondition Iterations= 10
UNET D2 ILUT Maximum Fill= 8
UNET D2 ILUT Tolerance=1E-08
UNET D1D2 MaxIter= 0
UNET D1D2 ZTol=0.01
UNET D1D2 QTol=0.1
UNET D1D2 MinQTol=1
Write IC File= 0
Write IC File at Fixed DateTime=0
Write IC File at Sim End=0
Echo Input=False
Echo Parameters=False
Echo Output=False
Write Detailed= 0
HDF Write Warmup=0
HDF Write Time Slices=0
HDF Flush=0
HDF Compression= 1
HDF Chunk Size= 1
HDF Spatial Parts= 1
HDF Use Max Rows=0
HDF Fixed Rows= 1
Calibration Method= 0
Calibration Iterations= 20
Calibration Max Change=0.05
Calibration Tolerance=0.2
Calibration Maximum=1.5
Calibration Minimum=0.5
Calibration Optimization Method= 1
WQ AD Non Conservative
WQ ULTIMATE=-1
WQ Max Comp Step=1HOUR
WQ Output Interval=15MIN
WQ Output Selected Increments= 0
WQ Output face flow=0
WQ Output face velocity=0
WQ Output face area=0
WQ Output face dispersion=0
WQ Output cell volume=0
WQ Output cell surface area=0
WQ Output cell continuity=0
WQ Output cumulative cell continuity=0
WQ Output face conc=0
WQ Output face dconc_dx=0
WQ Output face courant=0
WQ Output face peclet=0
WQ Output face adv mass=0
WQ Output face disp mass=0
WQ Output cell mass=0
WQ Output cell source sink temp=0
WQ Output nsm pathways=0
WQ Output nsm derived pathways=0
WQ Create Restart=0
WQ Fixed Restart=0
WQ System Summary=0
WQ Write To DSS=0
Sorting and Armoring Iterations= 10
XS Update Threshold= 0.02
Bed Roughness Predictor= 0
Hydraulics Update Threshold= 0.02
Energy Slope Method= 1
Volume Change Method= 1
Sediment Retention Method= 0
Sediment TS Multiplier= 1
Warm Up Method= 0
XS Weighting Method= 0
Number of US Weighted Cross Sections= 1
Number of DS Weighted Cross Sections= 1
Upstream XS Weight=0
Main XS Weight=1
Downstream XS Weight=0
Number of DS XS's Weighted with US Boundary= 1
Upstream Boundary Weight= 1
Weight of XSs Associated with US Boundary= 0
Number of US XS's Weighted with DS Boundary= 1
Downstream Boundary Weight= 0.5
Weight of XSs Associated with DS Boundary= 0.5
Percentile Method= 0
Sediment Output Level= 3
Mass or Volume Output= 0
Output Increment Type= 1
Profile and TS Output Increment= 1
Transport Output Increment 1
XS Output Flag= 0
XS Output Increment= 10
Read HDF5 Sediment Hotstart= 0
Sediment Hotstart Type= 0
Write Gradation File= 0
Read Gradation Hotstart= 0
Write HDF5 File= 1
Write Binary Output= 1
Write DSS Sediment File= 0
DSS Sediment Output Type= 1
SV Curve= 0
Specific Gage Flag= 0
Subcell Erosion Methods= 0
Subcell Deposition Methods= 0
Advection Scheme= 1
Matrix Solver= 0
Implicit Weighting Factor= 1
Maximum Outer Loop Convergence Iterations= 5
Convergence Maximum Absolute= 0.001
Convergence RMSE= 0.0001
Grain Fractions Max Abs Error= 0.001
Max Subgrid Regions= 1
Max Subgrid Length Scale= 3.402823E+38
Initial Layer Thickness= 3.402823E+38
Min Layer Thickness= 3.402823E+38
Max Layer Thickness= 3.402823E+38
Number of Layers= 5

--- MILLCK.f01 (steady flow) ---

Flow Title=Flow
Program Version=6.10
Number of Profiles= 6
Profile Names=01pct,10pct,04pct,02pct,0_2pct,01plus
River Rch & RM=OLDFLDFKT1,Main            ,3991
     610     323     429     516     851     902
River Rch & RM=MILLCK,Main            ,3991
     610     323     429     516     851     902
Boundary for River Rch & Prof#=MILLCK,Main            , 1
Up Type= 0
Dn Type= 3
Dn Slope=0.03498
Boundary for River Rch & Prof#=MILLCK,Main            , 2
Up Type= 0
Dn Type= 3
Dn Slope=0.03498
Boundary for River Rch & Prof#=MILLCK,Main            , 3
Up Type= 0
Dn Type= 3
Dn Slope=0.03498
Boundary for River Rch & Prof#=MILLCK,Main            , 4
Up Type= 0
Dn Type= 3
Dn Slope=0.03498
Boundary for River Rch & Prof#=MILLCK,Main            , 5
Up Type= 0
Dn Type= 3
Dn Slope=0.03498
Boundary for River Rch & Prof#=MILLCK,Main            , 6
Up Type= 0
Dn Type= 3
Dn Slope=0.03498
DSS Import GetInterval= 0
DSS Import GetPeak= 0
DSS Import FillOption= 0

--- MILLCK.g01 (geometry) ---

Geom Title=Geometry
Program Version=6.10

River Reach=MILLCK          ,Main
Reach XY= 30
2221359.55300002        496010.52221377.11900002496138.543000013
     2221366.434496182.5390000052221328.93799998496260.201000005
     2221317.851496340.2640000132221330.25700001496396.703000009
2221390.03700003496502.1879999942221394.62600002 496540.55400002
2221350.18200003496599.5209999982221327.55900003496652.244000003
2221292.26300003496830.9560000152221270.57699999496896.243000016
     2221106.765497116.760000005     2221093.116497173.220000014
2221104.29700002497274.413000003     2221226.699      497525.728
2221272.93099999497797.387000009      2221298.86497878.355000004
      2221516.92498155.9379999942221734.06800002498479.732999995
2221740.44600002498669.9899999952221807.93900003498929.731000036
2221869.39399998498978.7430000162221933.91500002499066.729000002
2221957.76900001499182.4850000142221995.25300004499273.081000015
2222098.14500003499321.9669999932222160.46700002499367.633000001
2222230.13800001 499443.657000022222259.71746475 499511.25792931

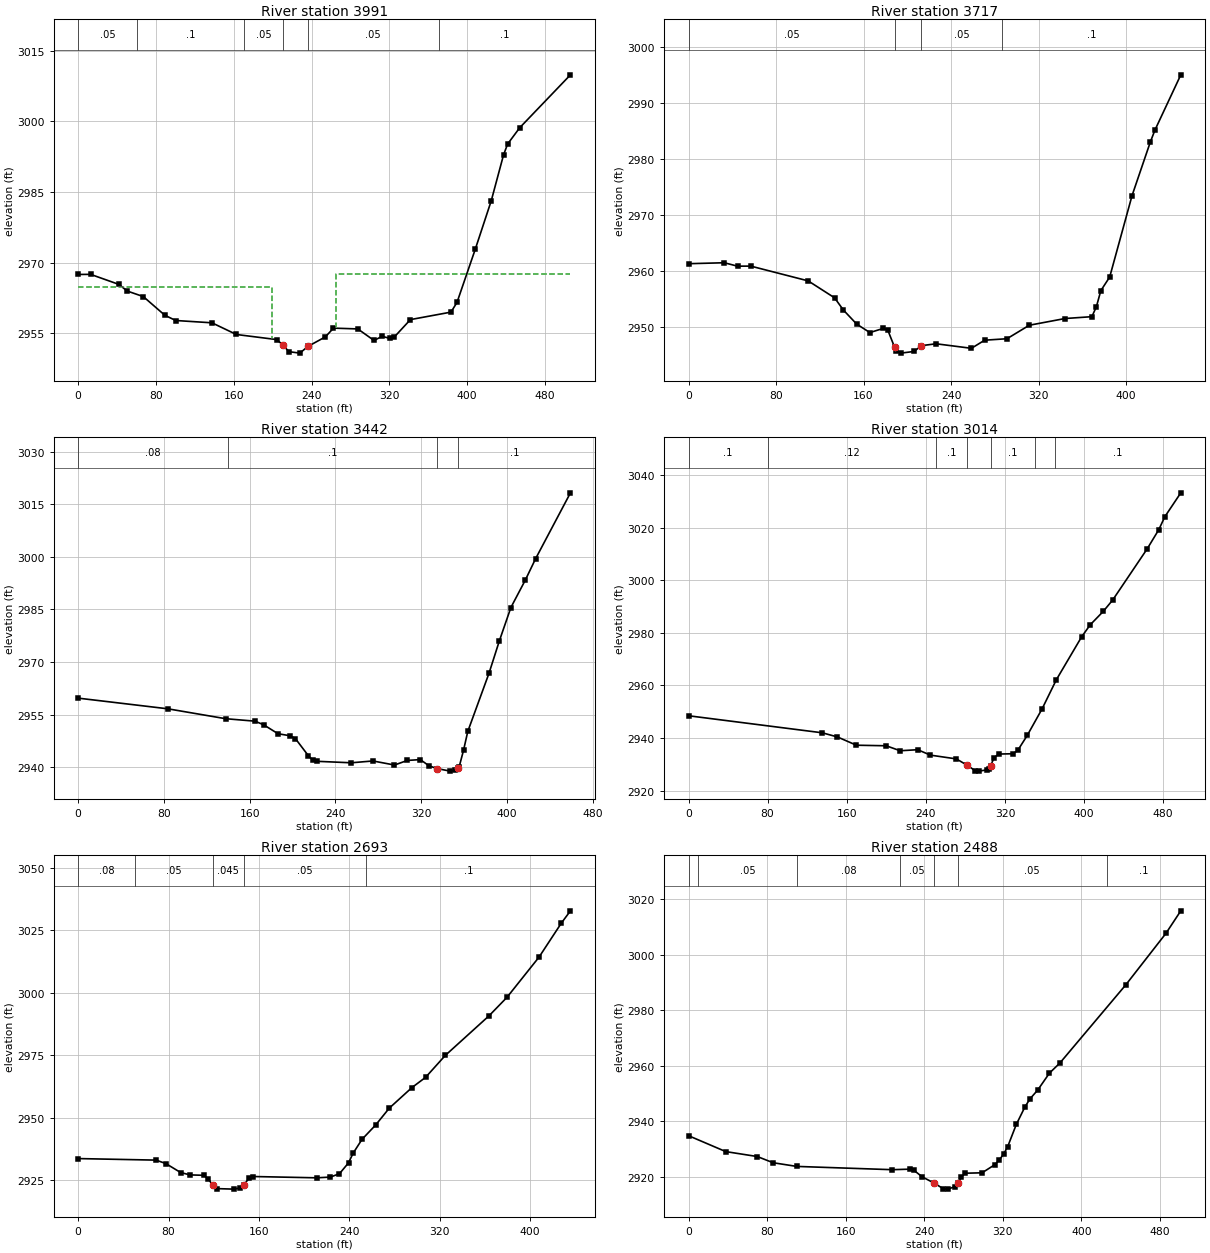
Type RM Length L Ch R = 1 ,3991    ,268.1,274.5,283.2
XS GIS Cut Line= 3
2221151.98156975496065.6130281362221181.28733963496074.627247098
 2221638.2986171495942.741173843
#Sta/Elev= 30
       0 2967.48    12.8  2967.5      42 2965.36    50.3 2963.97      67 2962.78
    89.1 2958.82   100.3  2957.7   137.6 2957.21   162.7 2954.73   204.4 2953.64
   210.62952.459   216.8 2951.08     228 2950.77   236.22952.179   254.3 2954.23
   262.6 2956.08   287.6 2955.91   304.3 2953.46   312.6 2954.34   320.9 2953.88
   325.1 2954.18   341.7 2957.89   383.4 2959.48   389.6 2961.53   408.4 2972.83
   424.9 2983.17   437.5 2992.88   441.7 2995.19   454.2 2998.66   506.3 3009.88
#Mann= 6 ,-1,0
       0     .05       0   60.66      .1       0  170.66     .05       0
   210.6    .045       0   236.2     .05       0  370.66      .1       0
#XS Ineff= 2 , 0
          199.42 2964.85  264.93         2967.48
Permanent Ineff=
       F       F
Bank Sta=210.6,236.2
XS Rating Curve= 0 ,0
Exp/Cntr=0.3,0.1

Type RM Length L Ch R = 1 ,3717    ,275.5,275.1,274
XS GIS Cut Line= 3
 2221127.7845154496258.7423806122221401.88473462  496294.9870377
2221571.78156472496259.875026146
#Sta/Elev= 30
       0 2961.38    32.7 2961.55    44.8 2960.94    56.9 2960.95   109.4 2958.31
   133.5 2955.29   141.6  2953.1   153.7  2950.6   165.8 2949.08   177.9 2949.82
     182  2949.6   188.3  2946.5     190 2945.73   194.1 2945.41   206.2 2945.71
   212.92946.742   226.3 2947.08   258.6 2946.27   270.7 2947.72   291.1 2947.98
   311.5 2950.39   344.2 2951.59   368.7 2951.92   372.8 2953.67   376.9 2956.57
     385    2959   405.4 2973.52   422.1 2983.09   426.4 2985.26     450 2995.11
#Mann= 4 ,-1,0
       0     .05       0   188.3    .045       0   212.9     .05       0
  286.49      .1       0
Bank Sta=188.3,212.9
XS Rating Curve= 0 ,0
Exp/Cntr(USF)=0,0
Exp/Cntr=0.3,0.1

Type RM Length L Ch R = 1 ,3442    ,420.1,427.5,435.5
XS GIS Cut Line= 3
2221109.77332387496381.1498743512221271.75006624496527.502688413
2221511.40090662496553.775511615
#Sta/Elev= 30
       0 2959.71    83.6 2956.67   137.7 2953.84     165 2953.14   173.1 2952.11
   186.5 2949.56   197.3    2949   202.7 2948.18   214.8  2943.3   218.7 2942.08
   222.8 2941.69   254.9 2941.27   275.1 2941.79   295.2 2940.63   307.2 2941.94
   319.3 2942.18   327.4 2940.41   334.82939.636   347.1 2938.89   351.5 2939.07
   354.82939.869   355.5 2940.06   359.6 2944.81   363.6 2950.21   383.4 2966.81
   393.1 2976.08   403.8 2985.55   417.2 2993.33   426.9 2999.49   459.4 3018.27
#Mann= 4 ,-1,0
       0     .08       0     140      .1       0   334.8    .045       0
   354.8      .1       0
Bank Sta=334.8,354.8
XS Rating Curve= 0 ,0
Exp/Cntr=0.3,0.1

Type RM Length L Ch R = 1 ,3014    ,331.4,320.9,306.8
XS GIS Cut Line= 3
2221066.51767911496706.539167667 2221203.3747371496904.524345643
2221417.55455429497046.780426628
#Sta/Elev= 30
       0 2948.44   135.3 2941.96   150.6 2940.38   169.8 2937.24   199.9 2937.03
     214 2935.14   231.8 2935.53   244.6 2933.47   270.8 2932.04   282.1 2929.57
   289.7 2927.58   293.7 2927.39   302.3  2927.9   304.1  2928.3   305.52929.408
   308.9 2932.48   313.7 2933.88   328.1    2934   332.9 2935.26   342.5 2940.95
   357.5 2951.03     372 2962.16   397.5 2978.43   406.2 2983.02   419.3 2988.08
   428.9 2992.43   463.9 3011.95   475.5 3019.16   481.7 3024.13   497.8 3033.19
#Mann= 7 ,-1,0
       0      .1       0      80     .12       0  250.68      .1       0
   282.1    .045       0   305.5      .1       0  350.68     .05       0
  370.68      .1       0
Bank Sta=282.1,305.5
XS Rating Curve= 0 ,0
Exp/Cntr=0.3,0.1

Type RM Length L Ch R = 1 ,2693    ,210.9,205.6,198
XS GIS Cut Line= 3
2220968.67966867497169.6084613062221056.42784675497206.766692569
2221396.22150695497182.981136355
#Sta/Elev= 30
       0 2933.61      69 2932.99    77.6 2931.62    90.7 2928.03      99 2927.07
   111.1 2926.91   115.1 2925.52   119.1    2923   123.1 2921.57   137.8 2921.37
   143.2 2921.83   146.82923.177   151.2 2925.65   155.2 2926.42   211.3  2925.9
   223.4  2926.2   231.4 2927.56   239.4  2931.9   243.4 2935.71   251.4 2941.34
   263.4 2947.05   275.5 2953.82   295.5 2962.04   307.6 2966.14   325.1 2974.94
   363.7 2990.76   379.7 2998.21   408.1 3014.33   427.9 3027.98   435.9 3032.86
#Mann= 5 ,-1,0
       0     .08       0      50     .05       0   119.1    .045       0
   146.8     .05       0  255.29      .1       0
Bank Sta=119.1,146.8
XS Rating Curve= 0 ,0
Exp/Cntr(USF)=0,0
Exp/Cntr=0.3,0.1

Type RM Length L Ch R = 1 ,2488    ,446.1,447.4,448.9
XS GIS Cut Line= 3
2220906.46484304497440.3854574772221101.13238715497421.649282328
2221382.22558054497301.559284471
#Sta/Elev= 30
       0 2934.85    37.9 2929.12      70 2927.34    86.1 2925.11   110.2 2923.78
   207.4  2922.6     225 2922.79   229.3 2922.43     238    2920   250.22917.754
   259.2 2915.78   264.1  2915.6   271.4 2916.52   274.4 2917.83   277.5  2919.8
   281.5 2921.33   298.9 2921.48     312 2924.44   316.3 2926.08   320.7 2928.15
     325 2930.94   333.7 2938.88   342.4 2945.13   347.6 2948.09   355.5 2951.28
   367.5  2957.4   378.1 2961.02   445.1 2989.14     486 3007.69   501.2 3015.84
#Mann= 7 ,-1,0
       0     .08       0      10     .05       0     110     .08       0
  215.57     .05       0   250.2    .045       0   274.4     .05       0
  425.57      .1       0
Bank Sta=250.2,274.4
XS Rating Curve= 0 ,0
Exp/Cntr=0.3,0.1

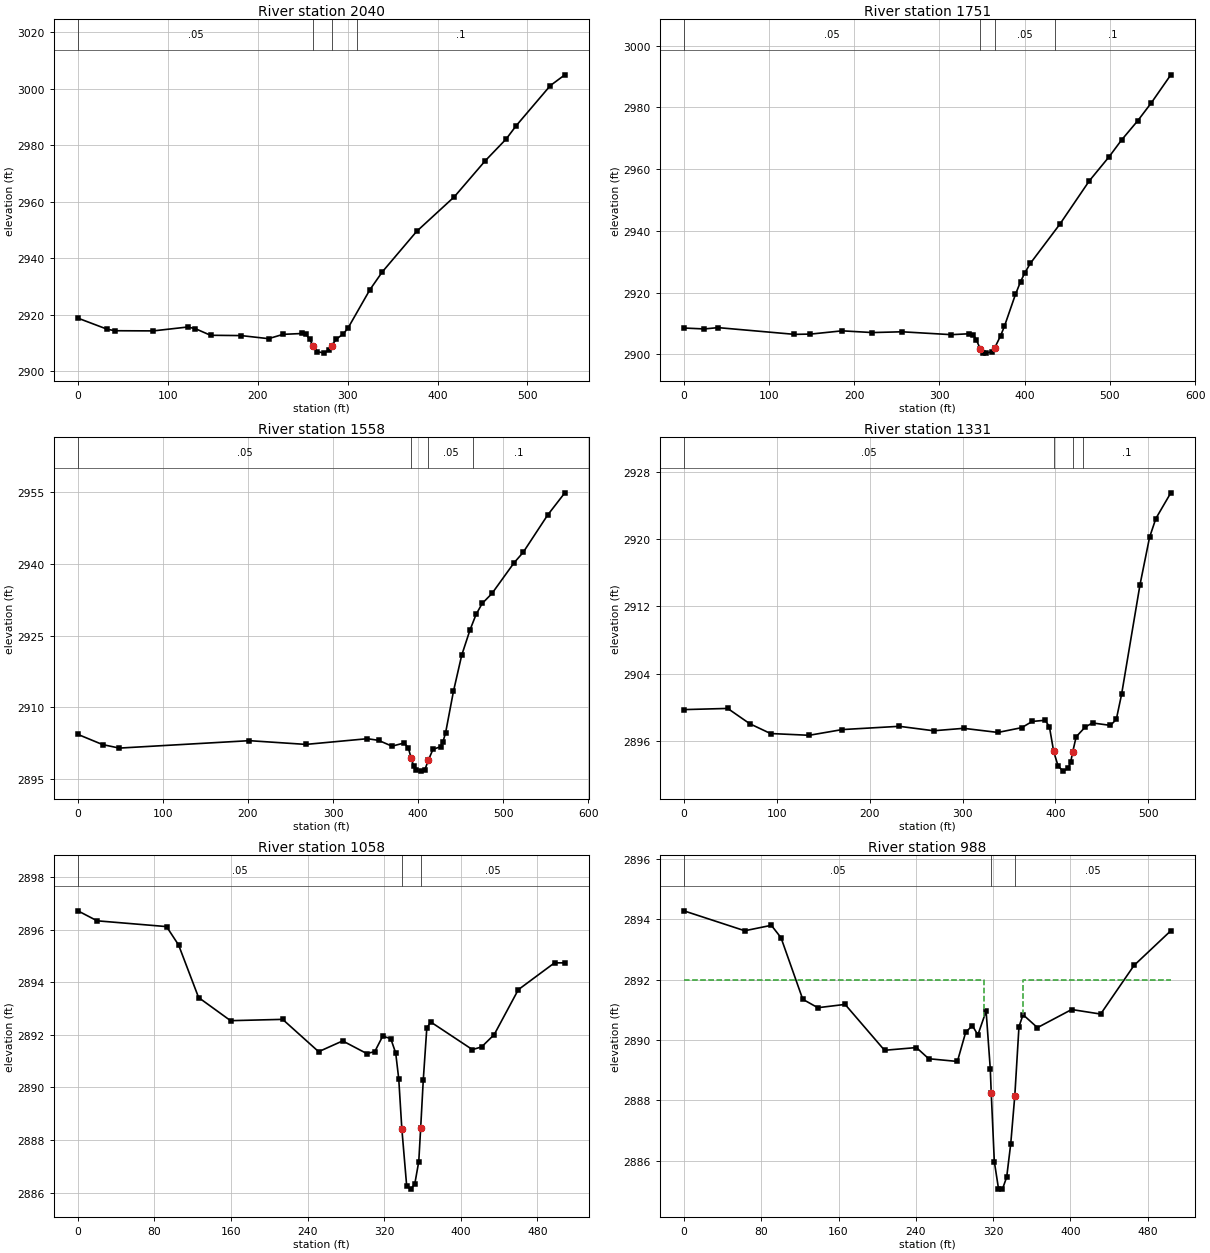
Type RM Length L Ch R = 1 ,2040    ,292,289.3,285.1
XS GIS Cut Line= 2
2221025.28673869497913.4080482622221535.35166629497731.221365436
#Sta/Elev= 30
       0  2918.8    32.8 2914.85    41.3 2914.34    83.8 2914.28     122 2915.65
   130.5 2915.09   147.5 2912.73   181.5 2912.62   212.1 2911.53   228.2 2913.06
   249.7 2913.36   253.7 2913.06   257.9 2911.26   261.7 2908.85   266.4 2906.94
   274.2 2906.41   279.2 2907.65   282.12909.066   287.6 2911.39   295.1  2913.2
   300.4 2915.27   324.8 2928.87   338.6 2935.18   376.8 2949.52   418.7 2961.77
   453.1 2974.52   476.3  2982.2   487.5 2986.93   525.5 3001.14   541.6 3004.94
#Mann= 4 ,-1,0
       0     .05       0   261.7    .045       0   282.1     .05       0
     310      .1       0
Bank Sta=261.7,282.1
XS Rating Curve= 0 ,0
Exp/Cntr(USF)=0,0
Exp/Cntr=0.3,0.1

Type RM Length L Ch R = 1 ,1751    ,192.9,192.6,192.1
XS GIS Cut Line= 3
 2221124.3095269498163.2258752232221248.76070286 498181.40413688
2221624.91088637497942.290079702
#Sta/Elev= 30
       0 2908.56    24.1 2908.26    40.1 2908.69   129.8 2906.51   148.6 2906.59
   185.8 2907.65   221.1 2907.09   255.9 2907.34   313.9 2906.41     335  2906.7
   339.9 2906.23   343.1 2904.84   347.8 2901.82   351.5 2900.59   354.4 2900.43
   362.1 2900.92   364.62902.024   371.8 2906.09   376.3 2909.19   389.2 2919.48
   395.2  2923.6     400 2926.35   406.6 2929.48   441.4 2942.23   475.8  2956.2
   499.3  2964.1   513.7 2969.45   532.7 2975.69   548.6 2981.47   571.5 2990.55
#Mann= 4 ,-1,0
       0     .05       0   347.8    .045       0   364.6     .05       0
  435.77      .1       0
Bank Sta=347.8,364.6
XS Rating Curve= 0 ,0
Exp/Cntr(USF)=0,0
Exp/Cntr=0.3,0.1

Type RM Length L Ch R = 1 ,1558    ,226.5,227.6,228.6
XS GIS Cut Line= 3
2221207.75074189498382.7743623492221291.85872512 498391.29745922
2221696.87943713498118.897060323
#Sta/Elev= 30
       0 2904.38    29.1 2902.25    48.7 2901.52   201.6 2903.07   268.1 2902.29
   340.4 2903.48   353.5 2903.14   369.3 2901.92   383.8 2902.59   388.6 2901.53
   391.92899.407   394.7 2897.85   397.6 2896.99   403.1 2896.71   407.9 2896.95
   412.22899.034   417.5 2901.25   426.4 2901.81   429.3 2902.86   432.4 2904.73
   441.6 2913.36   451.3  2920.9     461 2926.15   468.2 2929.42   475.4 2931.72
   486.9  2933.8   512.8 2940.19   523.6 2942.39   552.5 2950.21   572.6 2954.82
#Mann= 4 ,-1,0
       0     .05       0   391.9    .045       0   412.2     .05       0
  464.54      .1       0
Bank Sta=391.9,412.2
XS Rating Curve= 0 ,0
Exp/Cntr(USF)=0,0
Exp/Cntr=0.3,0.1

Type RM Length L Ch R = 1 ,1331    ,269.2,272.7,276
XS GIS Cut Line= 3
 2221331.3273755498605.1432405262221712.55241648498385.177135008
2221777.94774515498332.414994834
#Sta/Elev= 30
       0 2899.71    47.2 2899.85    70.9 2898.03    93.3 2896.86   134.9 2896.65
   170.4 2897.33   231.9 2897.72   268.8 2897.19   301.2 2897.48   338.1 2896.99
   363.7 2897.56     375  2898.3   388.9 2898.44   393.5 2897.67   398.1 2894.72
   402.8 2893.01   408.1 2892.38   413.5  2892.7   416.4 2893.44  418.44  2894.6
   422.3 2896.47   432.1 2897.64   439.9 2898.12   459.2 2897.83   465.5 2898.54
   471.2 2901.53     491 2914.58   501.3 2920.23   508.1 2922.48   524.2 2925.54
#Mann= 4 ,-1,0
       0     .05       0   398.1    .045       0  418.44     .05       0
     430      .1       0
Bank Sta=398.1,418.44
XS Rating Curve= 0 ,0
Exp/Cntr(USF)=0,0
Exp/Cntr=0.3,0.1

Type RM Length L Ch R = 1 ,1058    ,70.6,69.7,68.7
XS GIS Cut Line= 4
2221404.15668385 498729.032608612221487.36583571498734.696480019
2221823.59113268 498632.073497812221871.13149016498575.634092159
#Sta/Elev= 30
       0 2896.72    20.1 2896.34    92.6 2896.12   105.2 2895.42   126.1 2893.42
   159.5 2892.54   213.9 2892.59   251.5 2891.36   276.6 2891.77   301.7 2891.29
   310.1 2891.36   318.4 2891.95   326.8 2891.86     332 2891.31   335.2 2890.32
   338.4 2888.43   343.5 2886.24   347.7 2886.13   351.9 2886.32   356.1 2887.18
   358.12888.463   360.8 2890.28   364.5 2892.26   368.6 2892.49   412.1 2891.44
   421.7 2891.54   434.9 2892.01   460.1 2893.72   497.9 2894.74   508.7 2894.74
#Mann= 3 ,-1,0
       0     .05       0   338.4    .045       0   358.1     .05       0
Bank Sta=338.4,358.1
XS Rating Curve= 0 ,0
Exp/Cntr(USF)=0,0
Exp/Cntr=0.5,0.3

Type RM Length L Ch R = 1 ,988     ,33.4,32.8,32
XS GIS Cut Line= 4
2221442.22901415498794.0793566412221520.35372328498808.841584665
2221812.01904113 498705.448930092221888.63113273 498619.82837889
#Sta/Elev= 30
       0 2894.28      63 2893.62    90.5  2893.8   100.5 2893.39     123 2891.35
   138.6 2891.07   166.8 2891.18   207.6 2889.66   240.6 2889.75   253.3 2889.38
     283 2889.29   291.5 2890.25   298.4 2890.48   304.2 2890.17   312.7 2890.96
     317 2889.05     3182888.249   321.2 2885.97   325.5 2885.08   329.6 2885.06
     334 2885.46   338.2 2886.57   342.4 2888.16   346.7 2890.44   350.9 2890.84
   365.8 2890.41   401.2 2891.01   431.2 2890.86   465.7 2892.47   503.8 2893.62
#Mann= 3 ,0,0
       0     .05       0     318    .045       0   342.4     .05       0
#XS Ineff= 2 , 0
          310.72    2892   351.3            2892
Permanent Ineff=
       F       F
Bank Sta=318,342.4
XS Rating Curve= 0 ,0
Exp/Cntr(USF)=0,0
Exp/Cntr=0.5,0.3

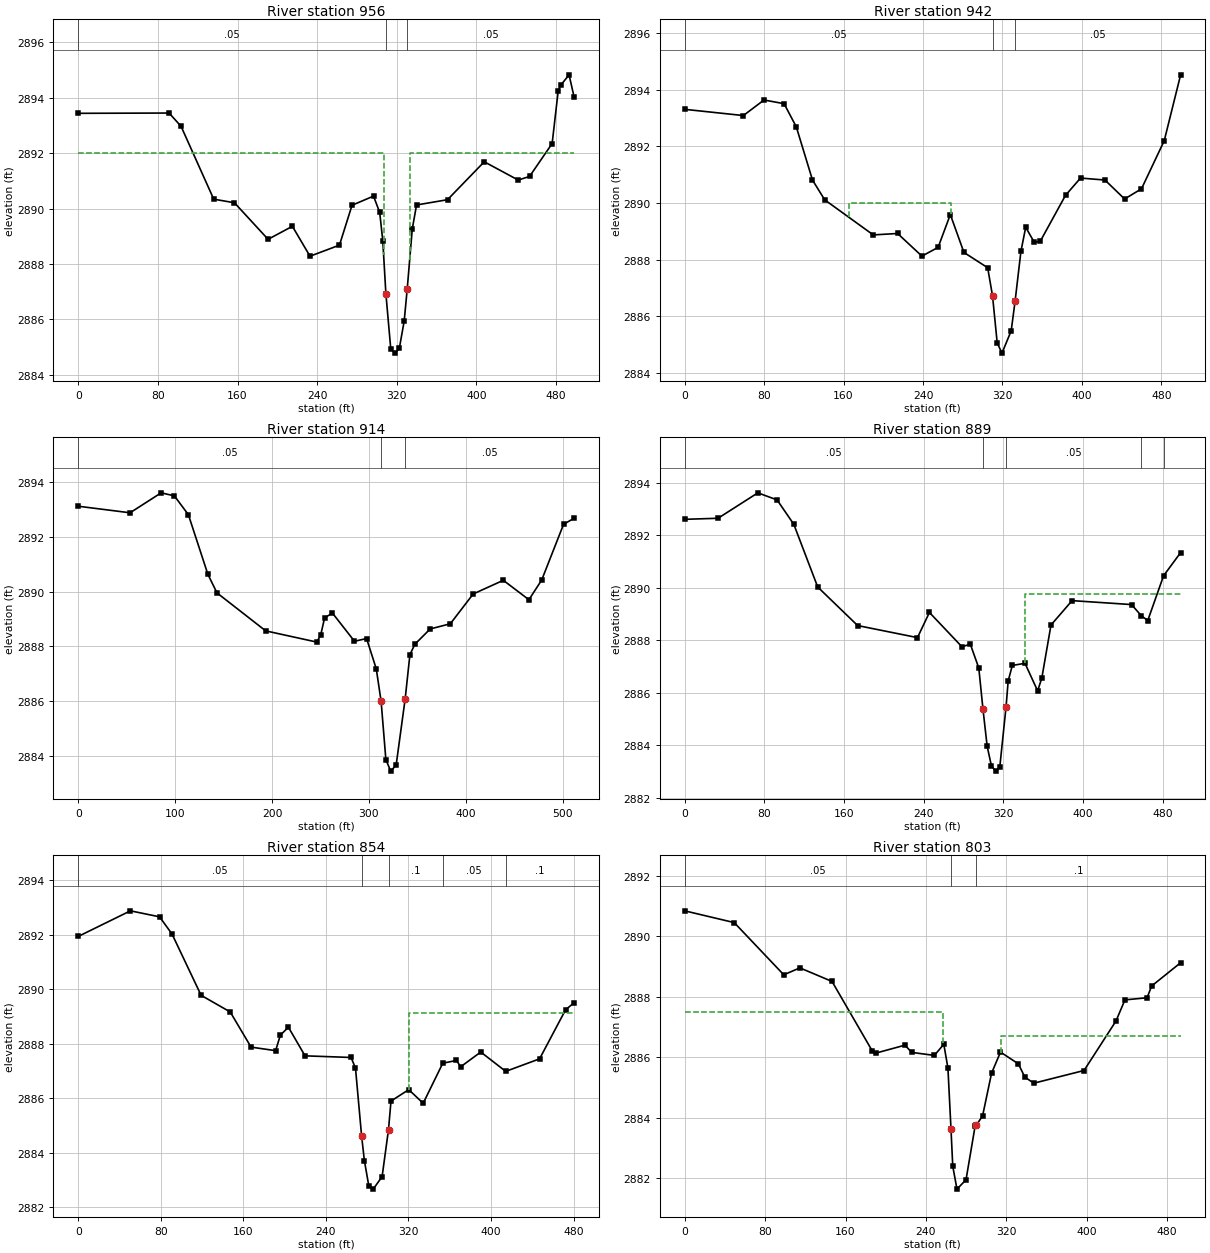
Type RM Length L Ch R = 1 ,956     ,16.5,13.8,10.3
XS GIS Cut Line= 5
2221456.91613169498816.1918012252221582.50488788498820.650573634
2221725.18560498498773.0903346042221786.86528997498747.823957619
2221904.27963008498646.015320943
#Sta/Elev= 30
       0 2893.44    91.3 2893.45   103.3 2892.97   136.1 2890.34   156.9 2890.21
   190.7 2888.89   215.1 2889.36   232.8 2888.28   262.4 2888.68     275 2890.12
   296.6 2890.45   302.8 2889.86   305.9 2888.84     309 2886.93   313.9 2884.94
   318.2 2884.78   322.5 2884.95   327.4 2885.94   330.4 2887.08   335.5 2889.26
   339.8 2890.13   370.9 2890.32   407.8 2891.69   441.9 2891.03   453.3 2891.16
     476 2892.35   482.1 2894.26   484.5 2894.45     493 2894.83   498.1 2894.02
#Mann= 3 ,-1,0
       0     .05       0     309    .045       0   330.4     .05       0
#XS Ineff= 2 , 0
          306.76    2892  332.85            2892
Permanent Ineff=
       F       F
Bank Sta=309,330.4
XS Rating Curve= 0 ,0
Exp/Cntr(USF)=0,0
Exp/Cntr=0.5,0.3

Type RM Length L Ch R = 1 ,942     ,29.4,28,26.6
XS GIS Cut Line= 6
2221460.47752376  498825.39701182221551.71212153498832.532678665
2221727.55534068498796.8543443442221793.81510442498753.530652668
 2221826.4352958498729.5751996242221904.41794082498653.631316569
#Sta/Elev= 30
       0 2893.31    59.1 2893.09    79.9 2893.64   100.1 2893.51   112.4 2892.69
   128.7 2890.81     141 2890.11   189.9 2888.87   214.4 2888.92   238.9 2888.12
   255.2 2888.43   267.5 2889.59   281.2 2888.25   305.1 2887.71     3102886.715
   314.7 2885.05   319.5 2884.69   328.8 2885.48   332.72886.522   338.6 2888.29
   343.4 2889.14     352 2888.61     358 2888.64   383.5 2890.27   398.6 2890.88
   423.2 2890.81     443 2890.14     460  2890.5   482.9  2892.2   499.4 2894.53
#Mann= 3 ,-1,0
       0     .05       0     310    .045       0   332.7     .05       0
#XS Ineff= 3 ,-1
     165     268    2890     268     293    2887     343     400  2886.5
Permanent Ineff=
       F       F       F
Bank Sta=310,332.7
XS Rating Curve= 0 ,0
Exp/Cntr(USF)=0,0
Exp/Cntr=0.5,0.3

Type RM Length L Ch R = 1 ,914     ,19.5,24.4,30.3
XS GIS Cut Line= 5
2221462.86116157498831.7975046572221556.49538216498839.228792006
2221743.02069461498821.393702369 2221802.4709934498777.549107013
2221913.19717489498666.822925519
#Sta/Elev= 30
       0 2893.13    53.5 2892.89    85.6 2893.62    99.2 2893.51   113.7 2892.82
   133.8 2890.64   143.2 2889.96   193.5 2888.57   246.3 2888.16   250.3 2888.43
   254.3 2889.05   262.4 2889.22   285.1 2888.19   297.6 2888.29   307.6 2887.18
   312.6 2885.99   317.5 2883.86   322.5 2883.44   328.1 2883.66   337.4 2886.08
   342.3  2887.7   347.4 2888.08   363.2 2888.64     384 2888.83   407.6 2889.92
   438.7 2890.42   465.1 2889.71   478.3 2890.43   500.9 2892.47   511.8 2892.69
#Mann= 3 ,-1,0
       0     .05       0   312.6    .045       0   337.4     .05       0
#XS Ineff= 2 , 0
          305.51    2887  341.45          2886.5
Permanent Ineff=
       F       F
Bank Sta=312.6,337.4
XS Rating Curve= 0 ,0
Exp/Cntr(USF)=0,0
Exp/Cntr=0.5,0.3

Type RM Length L Ch R = 1 ,889     ,36.6,35.7,34.5
XS GIS Cut Line= 4
2221474.75122133498849.6325942942221740.04817967498834.770019597
2221835.16865773498802.815483998  2221932.518522498713.640035815
#Sta/Elev= 30
       0 2892.61    33.5 2892.65    73.5 2893.62    92.8 2893.35   109.6 2892.42
   133.6 2890.03   173.7 2888.56   233.8  2888.1   245.8 2889.06   278.5 2887.75
   286.9 2887.85   295.4 2886.94   299.6 2885.37   303.8 2883.96     308 2883.22
   312.3 2883.01   316.5 2883.17   322.82885.472   324.9 2886.45   329.1 2887.04
   341.8 2887.12   354.5 2886.07   358.7 2886.56   367.9 2888.58   389.1 2889.51
   448.8 2889.36   458.5 2888.94   465.1 2888.75     481 2890.46   498.1 2891.34
#Mann= 5 ,-1,0
       0     .05       0   299.6    .045       0   322.8     .05       0
   458.5      .1       0     481     .05       0
#XS Ineff= 2 , 0
       0                   341.8       0 2889.78
Permanent Ineff=
       F       F
Bank Sta=299.6,322.8
XS Rating Curve= 0 ,0
Exp/Cntr(USF)=0,0
Exp/Cntr=0.3,0.1

Type RM Length L Ch R = 1 ,854     ,52.8,51,49
XS GIS Cut Line= 4
2221505.89625516498896.214680641 2221764.2899806498865.333388594
2221841.15933323498835.0518218062221955.03284708 498757.50467305
#Sta/Elev= 30
       0 2891.94    50.6 2892.88    78.8 2892.66    90.9 2892.03   119.1 2889.78
   147.3 2889.17   167.5 2887.88   191.3 2887.75   195.9 2888.32   203.7 2888.61
   219.8 2887.56   264.4  2887.5   268.7 2887.11   274.62884.629   277.3 2883.72
   281.6 2882.79   285.9 2882.67   294.5 2883.13   300.72884.856   303.1  2885.9
   320.3 2886.32   334.3 2885.82   353.3 2887.29   366.5 2887.39   370.7 2887.16
   390.1  2887.7   414.3 2886.99   447.1 2887.45   472.3 2889.25   480.6 2889.51
#Mann= 5 ,-1,0
       0     .05       0   274.6    .045       0   300.7      .1       0
   353.3     .05       0   414.3      .1       0
#XS Ineff= 2 , 0
       0                   320.3       0 2889.12
Permanent Ineff=
       F       F
Bank Sta=274.6,300.7
XS Rating Curve= 0 ,0
Exp/Cntr(USF)=0,0
Exp/Cntr=0.5,0.3

Type RM Length L Ch R = 1 ,803     ,40.1,39.4,39
XS GIS Cut Line= 4
2221533.59712927 498944.708689432221730.49566957498941.576435114
2221933.25320344498836.7018486332221962.61808765498775.175424564
#Sta/Elev= 30
       0 2890.85    49.3 2890.46    98.6 2888.73   114.6 2888.96   146.6 2888.51
   186.6 2886.21   190.6 2886.14   219.2  2886.4   225.8 2886.16   248.4 2886.06
   257.8 2886.43   261.9 2885.64  264.95 2883.62   266.7 2882.39   270.9 2881.63
   279.9 2881.94   288.9 2883.71     2902883.738   296.4 2884.06   305.3 2885.47
   314.2 2886.17     332 2885.78   338.4 2885.34   347.4 2885.14   397.3 2885.56
   429.1  2887.2     438  2887.9     460 2887.97   464.6 2888.36   493.4 2889.13
#Mann= 3 ,-1,0
       0     .05       0  264.95    .045       0     290      .1       0
#XS Ineff= 2 , 0
             257  2887.5  314.98          2886.7
Permanent Ineff=
       F       F
Bank Sta=264.95,290
XS Rating Curve= 0 ,0
Exp/Cntr(USF)=0,0
Exp/Cntr=0.5,0.3

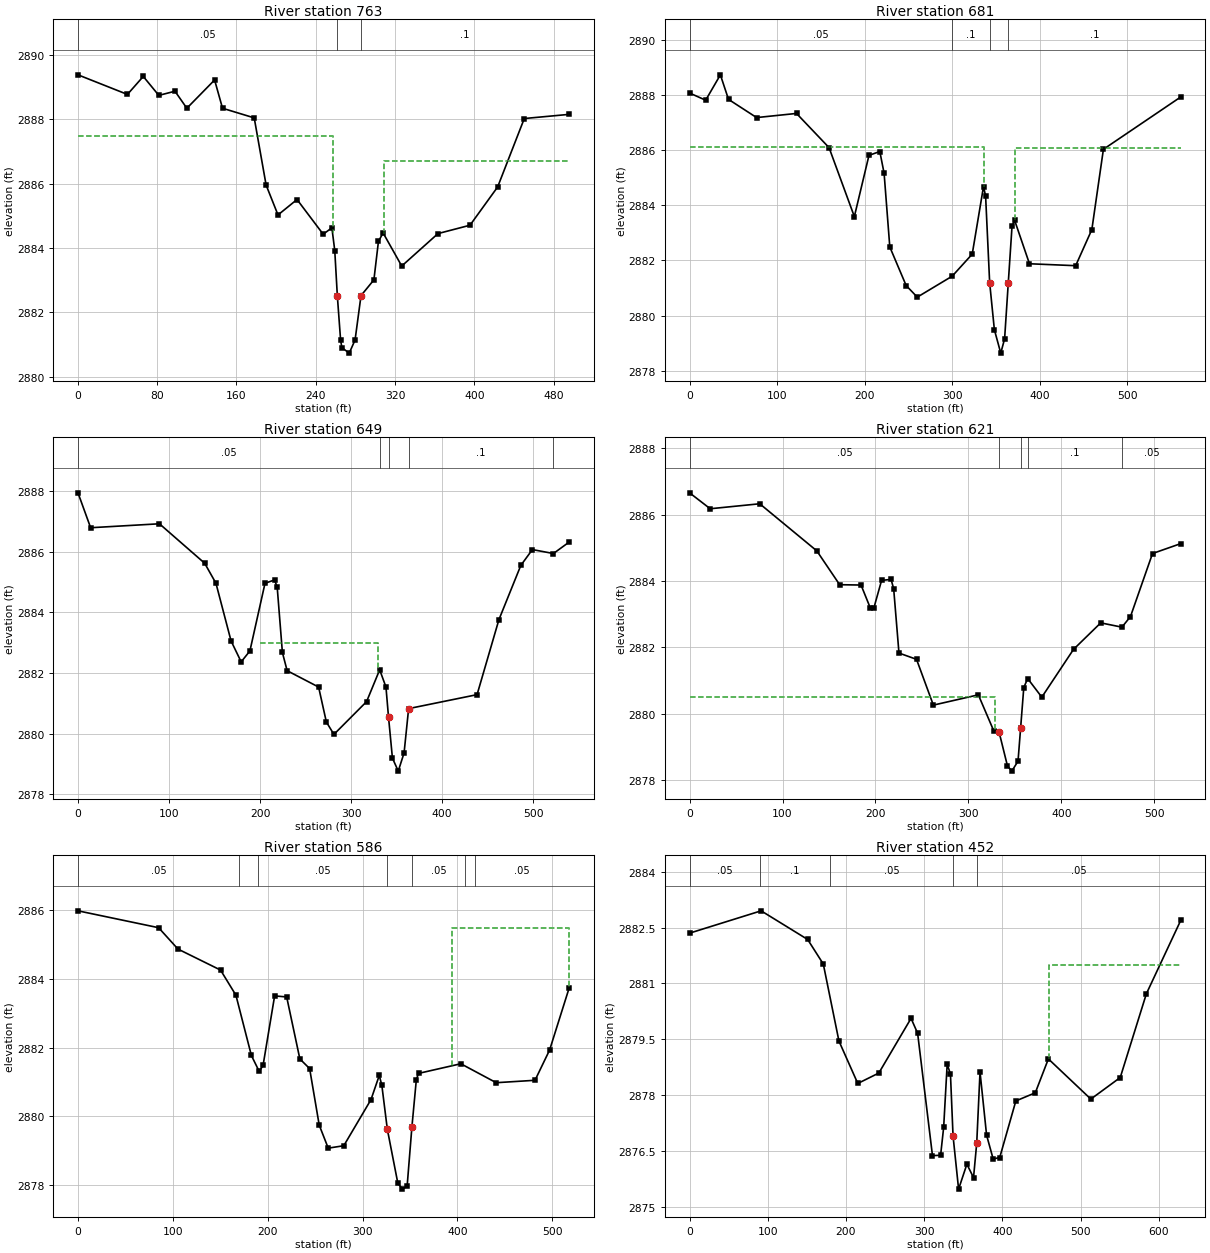
Type RM Length L Ch R = 1 ,763     ,83.8,82,78.3
XS GIS Cut Line= 4
2221554.30636428498972.3396471492221757.06389815498975.136302788
2221938.84651472498870.2617163072221979.39802149 498797.54866968
#Sta/Elev= 30
       0 2889.39    49.9 2888.78    65.9 2889.34    81.6 2888.75    97.9 2888.88
   109.9 2888.35   137.9 2889.23   145.9 2888.35   177.9 2888.05   189.9 2885.96
   201.9 2885.03   221.1 2885.51   247.5 2884.43   256.3 2884.63   259.2 2883.92
   261.8 2882.51   265.1 2881.13   266.4  2880.9   273.8 2880.73   279.7 2881.14
   285.7 2882.52   298.7 2883.01   303.3 2884.21     308 2884.47   326.8 2883.44
   363.4 2884.45   395.7 2884.71   423.6  2885.9   450.5 2888.03   495.9 2888.16
#Mann= 3 ,-1,0
       0     .05       0   261.8    .045       0   285.7      .1       0
#XS Ineff= 2 , 0
             257  2887.5  308.58          2886.7
Permanent Ineff=
       F       F
Bank Sta=261.8,285.7
XS Rating Curve= 0 ,0
Exp/Cntr(USF)=0,0
Exp/Cntr=0.5,0.3

Type RM Length L Ch R = 1 ,681     ,32.8,32.1,31.8
XS GIS Cut Line= 4
2221562.12872924499016.7287217722221772.86135739499072.907605654
  2221931.460407498951.1530311482221990.71154141498820.575853493
#Sta/Elev= 30
       0 2888.07    18.4 2887.81    35.2 2888.73    44.5 2887.84    76.6 2887.18
   122.2 2887.33   159.4 2886.09   188.3 2883.59     205 2885.81   217.4 2885.95
   222.3 2885.16   228.8 2882.49   247.5 2881.09   260.2 2880.67   300.1 2881.43
     323 2882.23   335.9 2884.68   338.3 2884.33   342.9  2881.2   348.3 2879.49
   355.6 2878.64     360 2879.16   364.2 2881.19   368.5 2883.25   371.5 2883.45
   388.4 2881.88   441.2 2881.81   459.7 2883.12   472.9 2886.03   561.4 2887.93
#Mann= 4 ,-1,0
       0     .05       0   300.1      .1       0   342.9    .045       0
   364.2      .1       0
#XS Ineff= 2 , 0
       0   335.9 2886.11   371.5       0 2886.08
Permanent Ineff=
       F       F
Bank Sta=342.9,364.2
XS Rating Curve= 0 ,0
Exp/Cntr(USF)=0,0
Exp/Cntr=0.5,0.3

Type RM Length L Ch R = 1 ,649     ,29,28.5,29
XS GIS Cut Line= 4
2221589.75880228499046.5946178982221793.77230897499101.481410333
2221941.55885546498982.2782000152222010.71633477498862.097001409
#Sta/Elev= 30
       0 2887.94    13.9 2886.79    89.5 2886.92   139.2 2885.62   151.6 2884.96
   168.2 2883.06   179.3 2882.37   188.9 2882.73   205.5 2884.96     216 2885.07
   218.9 2884.83   224.6 2882.68   229.8 2882.08   264.4 2881.54   272.9 2880.39
   281.2 2879.98   317.1 2881.06   331.5 2882.11   338.4 2881.54   341.22880.553
   345.5  2879.2   351.9 2878.77   358.3 2879.37   363.3 2880.83   438.5 2881.29
   462.5 2883.76   486.6 2885.55   499.3 2886.07   522.4 2885.94   539.8 2886.32
#Mann= 5 ,-1,0
       0     .05       0   331.5      .1       0   341.2    .045       0
   363.3      .1       0   522.4     .05       0
#XS Ineff= 3 ,-1
     200     330    2883     330   334.5  2880.5  370.43     450  2879.6
Permanent Ineff=
       F       F       F
Bank Sta=341.2,363.3
XS Rating Curve= 0 ,0
Exp/Cntr(USF)=0,0
Exp/Cntr=0.5,0.3

Type RM Length L Ch R = 1 ,621     ,33.5,34.1,35.2
XS GIS Cut Line= 4
2221606.49294888 499074.691889562221814.08220733499120.842046108
2221980.14550187498988.247346793 2222030.2279827498897.779186703
#Sta/Elev= 30
       0 2886.66    22.2 2886.18    75.5 2886.33   136.9 2884.91   161.5 2883.89
   184.5 2883.88   194.3  2883.2   198.4  2883.2   206.6 2884.02   216.8 2884.05
   219.6 2883.77   225.3 2881.83   244.2 2881.64   262.3 2880.26   310.7 2880.57
   327.5 2879.47   333.1 2879.44     342 2878.43   346.7 2878.27   353.4 2878.57
   356.2 2879.57   359.6 2880.79   363.8 2881.06     379  2880.5   413.1 2881.94
   442.4 2882.74   465.2 2882.61   474.4 2882.93   498.1 2884.83   528.6 2885.13
#Mann= 5 ,-1,0
       0     .05       0   333.1    .045       0   356.2     .05       0
   363.8      .1       0   465.2     .05       0
#XS Ineff= 2 , 0
           328.7  2880.5  359.42          2879.6
Permanent Ineff=
       F       F
Bank Sta=333.1,356.2
XS Rating Curve= 0 ,0
Exp/Cntr(USF)=0,0
Exp/Cntr=0.5,0.3

Type RM Length L Ch R = 1 ,586     ,129,134.8,141
XS GIS Cut Line= 4
2221620.70603554499096.3661494662221835.03942565499138.136329128
2222029.85061189499000.9477406642222058.63454729498946.882402276
#Sta/Elev= 30
       0 2885.97      85 2885.48   105.4 2884.86   150.3 2884.25   166.5 2883.52
   182.8 2881.77     191 2881.31   195.1 2881.48   207.3  2883.5     220 2883.47
   233.9 2881.67   244.2 2881.39   254.3 2879.75   263.8 2879.08   280.2 2879.15
   308.9 2880.49   317.6 2881.19   320.3 2880.91   326.1 2879.63   337.2 2878.06
   342.1 2877.89     347 2877.98     352 2879.69   356.7 2881.07     359 2881.25
   403.6 2881.53   440.9 2880.98   481.8 2881.05   497.2 2881.93   517.9 2883.74
#Mann= 7 ,-1,0
       0     .05       0     170      .1       0     190     .05       0
   326.1    .045       0     352     .05       0  408.37      .1       0
  418.37     .05       0
#XS Ineff= 2 , 0
                           394.2         2885.47
Permanent Ineff=
       F       F
Bank Sta=326.1,352
XS Rating Curve= 0 ,0
Exp/Cntr(USF)=0,0
Exp/Cntr=0.3,0.1

Type RM Length L Ch R = 1 ,452     ,145.6,131.5,117.6
XS GIS Cut Line= 4
2221621.36213252499204.0870823212221902.42602429499218.070360518
 2222038.0638228499174.7221981062222096.79359123498978.956303341
#Sta/Elev= 30
       0 2882.35    91.5 2882.95     151 2882.18     171 2881.52     191 2879.45
   215.1 2878.31     242 2878.59   283.2 2880.06   291.6 2879.66   310.6 2876.37
     321 2876.38   324.9 2877.13   329.4 2878.83   333.6 2878.56   336.9  2876.9
     344 2875.47   354.6 2876.14   363.1 2875.78   367.2 2876.71   371.4 2878.62
   379.8 2876.92   388.2 2876.28   396.6 2876.32   417.2 2877.84   442.1 2878.06
   458.8 2878.97   513.1 2877.89   550.7 2878.47   584.1 2880.72   628.2  2882.7
#Mann= 5 ,-1,0
       0     .05       0      90      .1       0     180     .05       0
   336.9    .045       0   367.2     .05       0
#XS Ineff= 2 , 0
                          459.23          2881.5
Permanent Ineff=
       F       F
Bank Sta=336.9,367.2
XS Rating Curve= 0 ,0
Exp/Cntr(USF)=0,0
Exp/Cntr=0.3,0.1

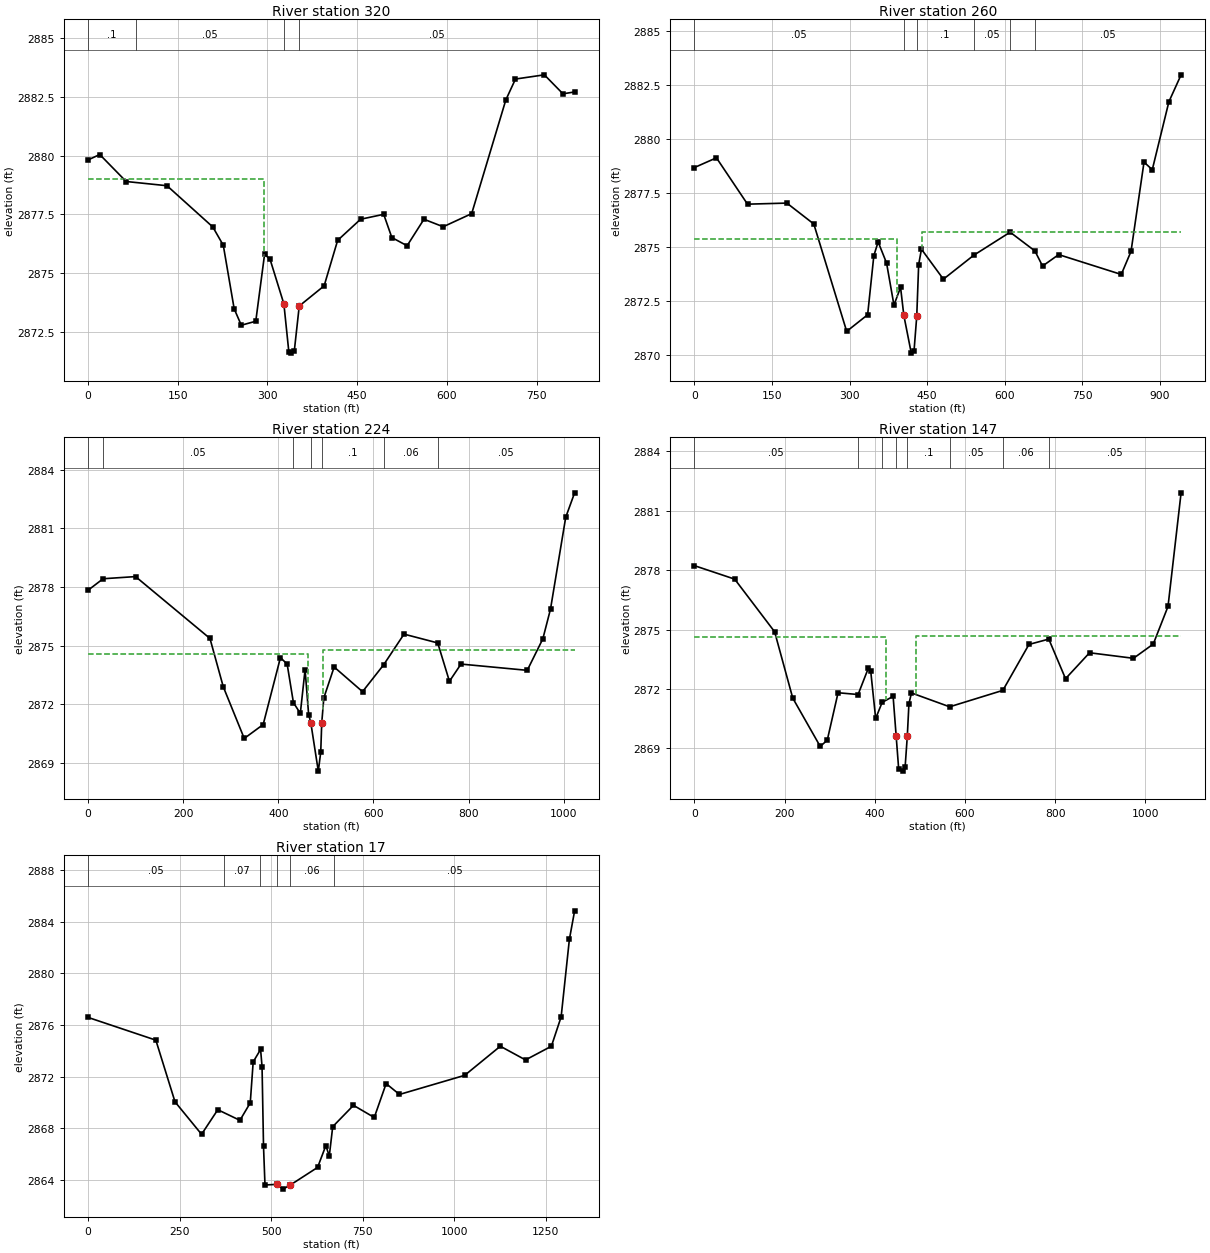
Type RM Length L Ch R = 1 ,320     ,57.9,60.2,61.3
XS GIS Cut Line= 4
2221724.52585871499317.1950461252222015.46201328499340.163689906
2222122.64901759499137.8208756422222155.46136585498846.884721078
#Sta/Elev= 30
       0 2879.82    19.7 2880.05    63.8  2878.9   132.1 2878.72   208.7 2876.96
   226.2 2876.18   244.4 2873.47   256.3 2872.77   280.5 2872.94   295.2 2875.79
   304.3 2875.59   327.5 2873.68   335.8 2871.63     339 2871.58     345 2871.69
   353.2 2873.59   394.8 2874.45   417.4 2876.39   455.7 2877.29   494.4  2877.5
     508 2876.51   533.5 2876.16   561.7 2877.29   593.9 2876.97   641.5 2877.53
   698.6 2882.38   714.7 2883.27     763 2883.45   794.1 2882.64   813.6 2882.72
#Mann= 4 ,-1,0
       0      .1       0      80     .05       0   327.5    .045       0
   353.2     .05       0
#XS Ineff= 2 , 0
          294.69    2879
Permanent Ineff=
       F       F
Bank Sta=327.5,353.2
XS Rating Curve= 0 ,0
Exp/Cntr(USF)=0,0
Exp/Cntr=0.5,0.3

Type RM Length L Ch R = 1 ,260     ,36.1,35.5,35.1
XS GIS Cut Line= 4
2221705.75099398499360.5550839342222054.53045361499379.712981139
2222206.64003374499147.3980311762222193.14781218498833.616110348
#Sta/Elev= 30
       0 2878.68    42.5 2879.13   102.6 2876.98   178.7 2877.03   230.8 2876.06
   294.4 2871.08   334.9 2871.85   346.9 2874.59   355.2 2875.23   371.5 2874.25
   385.8  2872.3   398.6 2873.12   404.9 2871.82   419.3 2870.07   424.6 2870.16
  429.89 2871.78   433.6 2874.18     439 2874.89   481.4  2873.5   540.1 2874.61
   610.5 2875.68   658.4 2874.81   673.2 2874.11   704.4 2874.64   825.4 2873.72
   844.3 2874.79   869.4 2878.93   885.4 2878.58   917.5 2881.73   941.1 2882.98
#Mann= 6 ,-1,0
       0     .05       0   404.9    .045       0  429.89      .1       0
   540.1     .05       0   610.5     .06       0   658.4     .05       0
#XS Ineff= 2 , 0
           391.3 2875.37  439.61         2875.67
Permanent Ineff=
       F       F
Bank Sta=404.9,429.89
XS Rating Curve= 0 ,0
Exp/Cntr(USF)=0,0
Exp/Cntr=0.5,0.3

Type RM Length L Ch R = 1 ,224     ,72.1,77.8,82
XS GIS Cut Line= 4
2221680.44474337499379.8512386022222081.03429709499407.787671909
2222234.35983803499159.8641309332222212.98915561498830.572528745
#Sta/Elev= 30
       0 2877.83    31.8 2878.42     100 2878.53   256.4 2875.37   284.4  2872.9
   328.5 2870.26   368.3 2870.97   404.6 2874.39   418.7 2874.06   431.9 2872.09
   446.4 2871.54   456.4 2873.78   463.9 2871.48   468.4 2871.07   484.2 2868.59
   489.3 2869.55  491.41 2871.04   495.8 2872.33   517.5 2873.91   577.2 2872.65
   621.8 2874.03   664.4 2875.59   735.3 2875.14   759.9 2873.18   784.2 2874.06
   923.5 2873.74   956.3 2875.35   972.4 2876.87  1004.4 2881.56  1023.1 2882.81
#Mann= 7 ,-1,0
       0      .1       0    31.8     .05       0   431.9      .1       0
   468.4    .045       0  491.41      .1       0   621.8     .06       0
   735.3     .05       0
#XS Ineff= 2 , 0
          462.32 2874.56  493.69         2874.78
Permanent Ineff=
       F       F
Bank Sta=468.4,491.41
XS Rating Curve= 0 ,0
Exp/Cntr(USF)=0,0
Exp/Cntr=0.5,0.3

Type RM Length L Ch R = 1 ,147     ,124.5,129.5,132.8
XS GIS Cut Line= 4
2221747.49450249499405.788386424 2222120.4615277499447.350694219
2222302.02318807499277.8202282142222227.64853202498828.291057064
#Sta/Elev= 30
       0 2878.23    89.2 2877.55   177.8 2874.89     218 2871.54   278.9  2869.1
   294.5 2869.41   318.5 2871.81   362.9 2871.72   385.8 2873.06   390.8 2872.93
   401.9 2870.51   416.2 2871.32   440.6 2871.63  447.42  2869.6     453 2867.94
   462.4 2867.85   467.2 2868.05  472.02  2869.6   475.7 2871.26   481.3  2871.8
     566  2871.1     684 2871.93   741.9 2874.25   785.9 2874.52     823 2872.52
   876.3 2873.83   973.7 2873.55  1017.6 2874.27  1050.3 2876.17  1079.3 2881.91
#Mann= 8 ,-1,0
       0     .05       0   362.9     .07       0   416.2      .1       0
  447.42    .045       0  472.02      .1       0     566     .05       0
     684     .06       0   785.9     .05       0
#XS Ineff= 2 , 0
       0   424.1 2874.61  491.57       0 2874.66
Permanent Ineff=
       F       F
Bank Sta=447.42,472.02
XS Rating Curve= 0 ,0
Exp/Cntr(USF)=0,0
Exp/Cntr=0.3,0.1

Type RM Length L Ch R = 1 ,17      ,,,
XS GIS Cut Line= 4
2221728.18517821499462.8386627182222214.64782424499518.741922882
2222362.90510024499431.4001406432222260.20432282498772.834137599
#Sta/Elev= 30
       0 2876.59   185.2 2874.83   237.5 2870.06     310 2867.55   354.3 2869.45
   414.7 2868.63   442.9 2869.98   450.9 2873.15   471.1 2874.11   475.1 2872.79
   479.1 2866.62   483.1 2863.63   516.4 2863.68   532.1 2863.31   551.8 2863.62
   626.7 2864.99   649.3 2866.68   658.6 2865.86     668 2868.14   724.7 2869.79
   781.4 2868.85   813.8 2871.47   850.2 2870.63  1028.3 2872.11  1125.5 2874.36
  1194.3  2873.3  1264.9 2874.36  1291.5 2876.63    1314 2882.62  1328.3 2884.83
#Mann= 6 ,-1,0
       0     .05       0     370     .07       0     470     .06       0
   516.4    .045       0   551.8     .06       0  671.74     .05       0
Bank Sta=516.4,551.8
XS Rating Curve= 0 ,0
Exp/Cntr(USF)=0,0
Exp/Cntr=0.3,0.1
LCMann Table=0

Chan Stop Cuts=-1
Use User Specified Reach Order=0
Composite Channel Slope=5